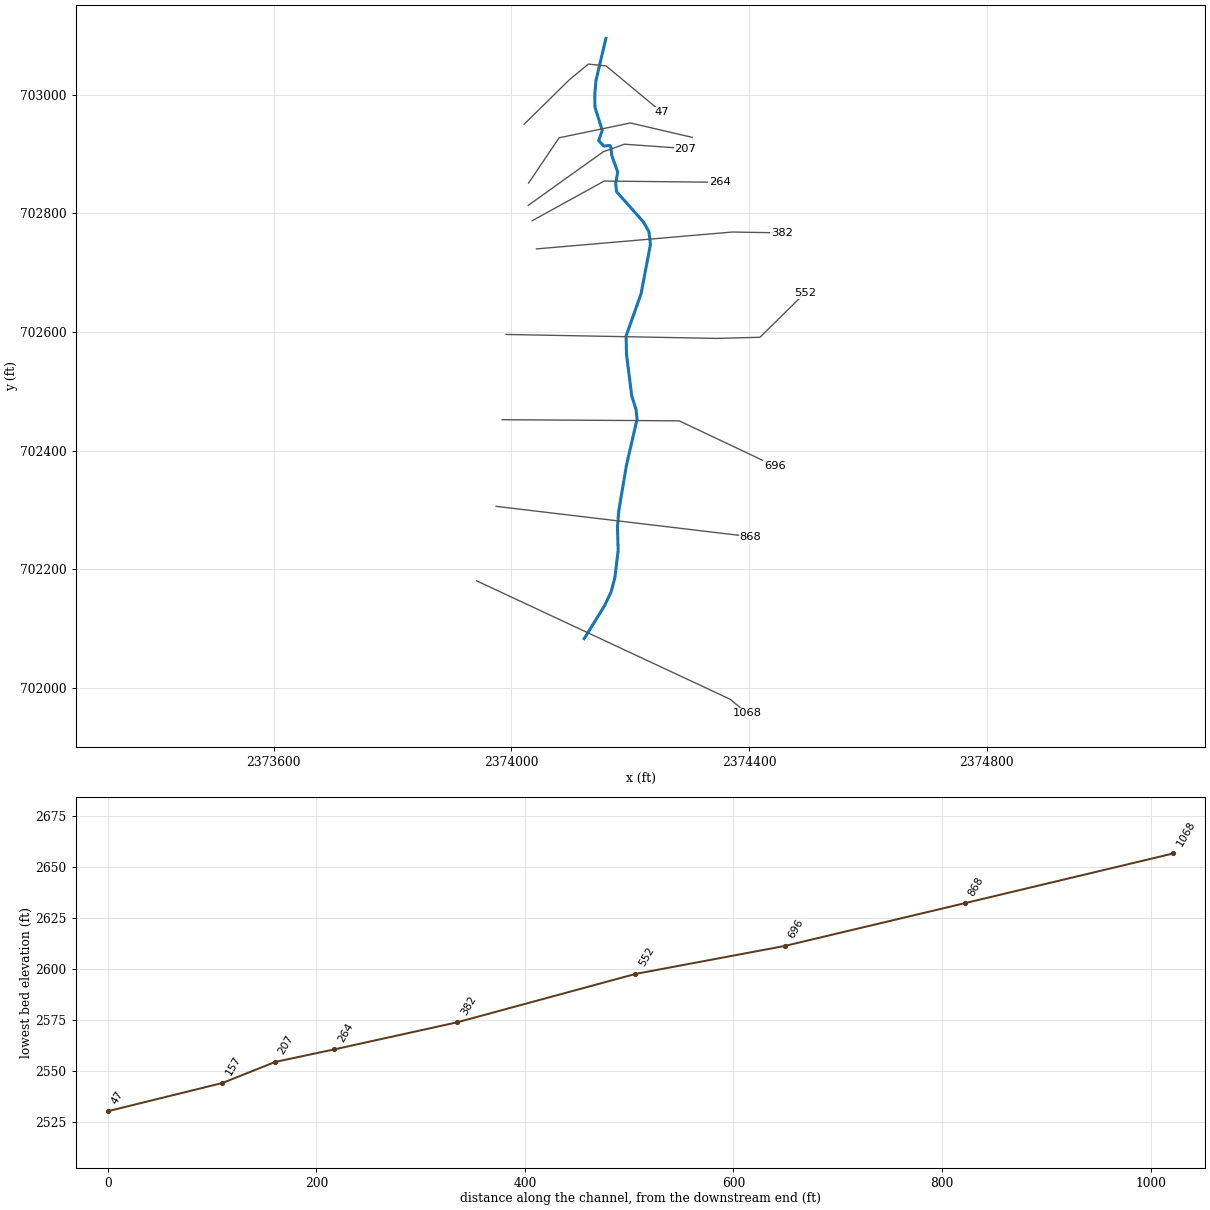
--- SCKLCKRN.prj (project) ---

Proj Title=SCKLCKRN
Current Plan=p01
Default Exp/Contr=0,0
English Units
Geom File=g01
Flow File=f01
Plan File=p01
BEGIN DESCRIPTION:
----------MODEL BY WOOD PLC 2022----------
AFH study
Randolph County, WV
HEC-RAS Version: RAS 6.2
Vertical Datum: NAVD88
Projection: NAD 1983 StatePlane West Virginia S FIPS 4702 (US Feet)
Terrain: 1-meter LIDAR (FEMA Region III 3DEP collected 2016-2018)
Land Use: 2019 NLCD
Hydrologic Method:
WV SIR2010-5033 regression equations
Additional Model Notes:
None
END DESCRIPTION:
DSS Export Rating Curves= 0
DSS Export Rating Curve Sorted= 0
DSS Export Volume Flow Curves= 0
DXF OffsetX= 0
DXF OffsetY= 0
DXF ScaleX= 0
DXF ScaleY= 0

--- SCKLCKRN.p01 (plan) ---

Plan Title=Floodplain
Program Version=6.20
Short Identifier=Floodplain
Geom File=g01
Flow File=f01
Subcritical Flow
K Sum by GR= 0
Std Step Tol= 0.01
Critical Tol= 0.01
Num of Std Step Trials= 20
Max Error Tol= 0.3
Flow Tol Ratio= 0.001
Split Flow NTrial= 30
Split Flow Tol= 0.02
Split Flow Ratio= 0.02
Log Output Level= 0
Friction Slope Method= 1
Unsteady Friction Slope Method= 2
Unsteady Bridges Friction Slope Method= 1
Parabolic Critical Depth
Global Vel Dist= 0 , 0 , 0
Global Log Level= 0
CheckData=True
Encroach Param=-1 ,0,0, 0
Mapping Interval=1HOUR
Computation Time Step Use Courant=        0
Computation Time Step Use Time Series=    0
Computation Time Step Count To Double=0
Computation Time Step Max Doubling=0
Computation Time Step Max Halving=0
Computation Time Step Residence Courant=0
Run HTab= 0
Run UNet= 0
Run Sediment= 0
Run PostProcess= 0
Run WQNet= 0
Run RASMapper=-1
UNET Theta= 0
UNET Theta Warmup= 0
UNET ZTol= 0
UNET ZSATol= 0
UNET MxIter= 0
UNET Max Iter WO Improvement= 0
UNET MaxInSteps= 0
UNET DtIC= 0
UNET DtMin= 0
UNET MaxCRTS= 0
UNET WFStab= 0
UNET SFStab= 0
UNET WFX= 1
UNET SFX= 1
UNET Gravity=32.174
UNET 1D Methodology=Finite Difference
UNET DSS MLevel= 1
UNET Pardiso=0
UNET DZMax Abort= 0
UNET Use Existing IB Tables= 0
UNET Froude Reduction=False
UNET Froude Limit= 0
UNET Froude Power= 0
UNET D1 Cores= 0
UNET WindReference=Eulerian
UNET WindDragFormulation=Hsu (1988)
UNET D2 Coriolis=0
UNET D2 Cores= 0
UNET D2 Theta= 1
UNET D2 Theta Warmup= 1
UNET D2 Z Tol= 0.01
UNET D2 Volume Tol= 0.01
UNET D2 Max Iterations= 20
UNET D2 Equation= 0
UNET D2 RampUpFraction=0.1
UNET D2 TimeSlices= 1
UNET D2 Turbulence Formulation=Non-Conservative (original)
UNET D2 Eddy Viscosity=0.3
UNET D2 Transverse Eddy Viscosity=0.1
UNET D2 Smagorinsky Mixing=0
UNET D2 BCVolumeCheck=0
UNET D2 Cores=0
UNET D2 SolverType=PARDISO (Direct)
UNET D2 Minimum Iterations= 2147483647
UNET D2 Maximum Iterations= 2147483647
UNET D2 Restart Number= 10
UNET D2 Relaxation Coeff=1.3
UNET D2 SOR Precondition Iterations= 10
UNET D2 ILUT Maximum Fill= 8
UNET D2 ILUT Tolerance=1E-08
UNET D1D2 MaxIter= 0
UNET D1D2 ZTol=0.01
UNET D1D2 QTol=0.1
UNET D1D2 MinQTol=1
Write IC File= 0
Write IC File at Fixed DateTime=0
Write IC File at Sim End=0
Echo Input=False
Echo Parameters=False
Echo Output=False
Write Detailed= 0
HDF Write Warmup=0
HDF Write Time Slices=0
HDF Flush=0
HDF Compression= 1
HDF Chunk Size= 1
HDF Spatial Parts= 1
HDF Use Max Rows=0
HDF Fixed Rows= 1
Calibration Method= 0
Calibration Iterations= 20
Calibration Max Change=0.05
Calibration Tolerance=0.2
Calibration Maximum=1.5
Calibration Minimum=0.5
Calibration Optimization Method= 1
WQ AD Non Conservative
WQ ULTIMATE=-1
WQ Max Comp Step=1HOUR
WQ Output Interval=15MIN
WQ Output Selected Increments= 0
WQ Output face flow=0
WQ Output face velocity=0
WQ Output face area=0
WQ Output face dispersion=0
WQ Output cell volume=0
WQ Output cell surface area=0
WQ Output cell continuity=0
WQ Output cumulative cell continuity=0
WQ Output face conc=0
WQ Output face dconc_dx=0
WQ Output face courant=0
WQ Output face peclet=0
WQ Output face adv mass=0
WQ Output face disp mass=0
WQ Output cell mass=0
WQ Output cell source sink temp=0
WQ Output nsm pathways=0
WQ Output nsm derived pathways=0
WQ Create Restart=0
WQ Fixed Restart=0
WQ System Summary=0
WQ Write To DSS=0
Sorting and Armoring Iterations= 10
XS Update Threshold= 0.02
Bed Roughness Predictor= 0
Hydraulics Update Threshold= 0.02
Energy Slope Method= 1
Volume Change Method= 1
Sediment Retention Method= 0
Sediment TS Multiplier= 1
Warm Up Method= 0
XS Weighting Method= 0
Number of US Weighted Cross Sections= 1
Number of DS Weighted Cross Sections= 1
Upstream XS Weight=0
Main XS Weight=1
Downstream XS Weight=0
Number of DS XS's Weighted with US Boundary= 1
Upstream Boundary Weight= 1
Weight of XSs Associated with US Boundary= 0
Number of US XS's Weighted with DS Boundary= 1
Downstream Boundary Weight= 0.5
Weight of XSs Associated with DS Boundary= 0.5
Percentile Method= 0
Sediment Output Level= 3
Mass or Volume Output= 0
Output Increment Type= 1
Profile and TS Output Increment= 1
Transport Output Increment 1
XS Output Flag= 0
XS Output Increment= 10
Read HDF5 Sediment Hotstart= 0
Sediment Hotstart Type= 0
Write Gradation File= 0
Read Gradation Hotstart= 0
Write HDF5 File= 1
Write Binary Output= 1
Write DSS Sediment File= 0
DSS Sediment Output Type= 1
SV Curve= 0
Specific Gage Flag= 0
Subcell Erosion Methods= 0
Subcell Deposition Methods= 0
Advection Scheme= 1
Matrix Solver= 0
Implicit Weighting Factor= 1
Maximum Outer Loop Convergence Iterations= 5
Convergence Maximum Absolute= 0.001
Convergence RMSE= 0.0001
Grain Fractions Max Abs Error= 0.001
Max Subgrid Regions= 1
Max Subgrid Length Scale= 3.402823E+38
Initial Layer Thickness= 3.402823E+38
Min Layer Thickness= 3.402823E+38
Max Layer Thickness= 3.402823E+38
Number of Layers= 5

--- SCKLCKRN.f01 (steady flow) ---

Flow Title=Flow
Program Version=6.20
Number of Profiles= 1
Profile Names=P100yr
River Rch & RM=SCKLCKRN,Main,1068
     310
Boundary for River Rch & Prof#=SCKLCKRN,Main            , 1
Up Type= 0
Dn Type= 3
Dn Slope=0.1256
DSS Import GetInterval= 0
DSS Import GetPeak= 0
DSS Import FillOption= 0

--- SCKLCKRN.g01 (geometry) ---

Geom Title=Geometry
Program Version=6.20

River Reach=SCKLCKRN        ,Main
Reach XY= 30
2374122.53399999702082.9950000052374156.82200001702138.550999999
2374167.82900003702161.940000013     2374174.183702185.859999999
2374179.71800002702231.9280000032374178.52300003 702271.36300002
2374180.69300003702297.8390000022374193.71400002702375.530000001
2374211.50899999702452.8740000132374209.82400002702469.135000005
     2374202.581702492.2130000142374193.71400002702562.596000001
2374193.16299999702593.3470000182374218.28399999702664.454000011
     2374234.079702747.4919999992374231.47500001702769.193000004
2374221.92600003702785.6860000042374177.04860474702836.347237257
 2374175.5383536702851.017609344     2374178.957702869.453999996
2374168.97419731702897.5299235072374167.23331447702912.302654168
2374165.64627621702914.2423675872374155.59503395 702913.36067967
2374146.95449236 702922.35389643 2374152.9499702702939.811317201
2374140.76300001702978.3949999962374140.32900003702999.662000015
2374142.49900004703024.4010000082374159.09934679703094.886995965

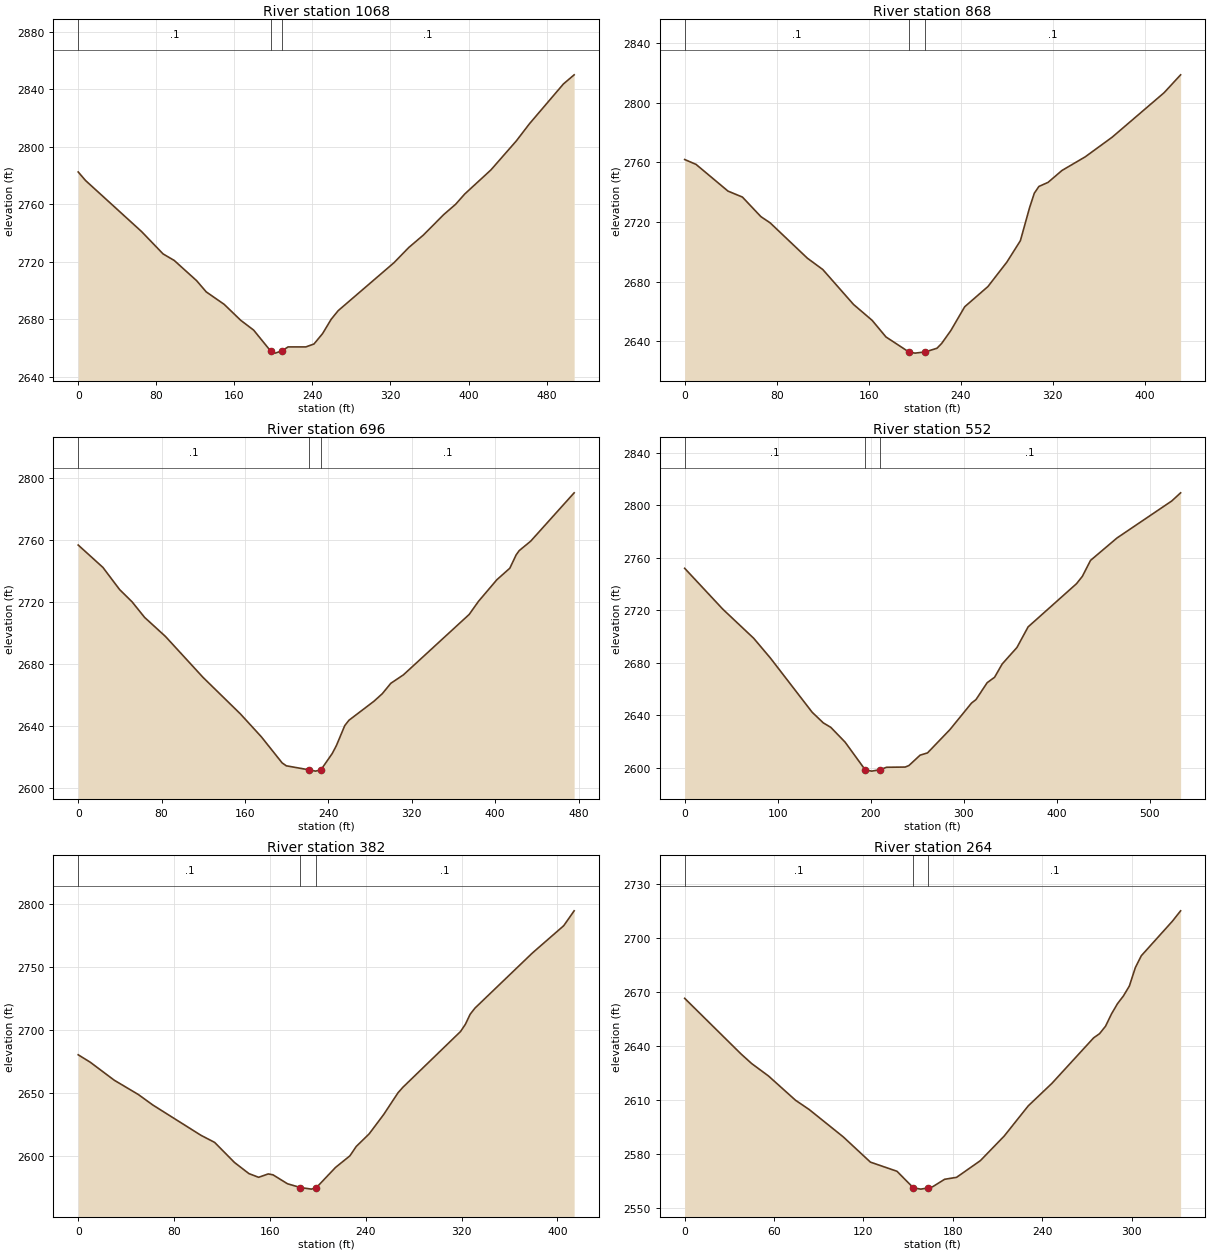
Type RM Length L Ch R = 1 ,1068    ,196.8,200.3,200.9
XS GIS Cut Line= 3
2373941.35464202702180.5706592532374368.41658689701980.775597325
2374396.51276747701957.049933721
#Sta/Elev= 30
       0 2782.48     7.5 2776.55    64.9 2741.08      87  2725.5    98.4 2720.98
   121.3 2706.94   131.2 2699.12   149.6 2690.46   166.5  2679.4   179.8 2672.55
   197.2 2658.02   201.8 2656.55  208.35 2657.96   215.1 2660.87   233.3 2660.87
   241.6 2662.89   250.4 2670.08   259.2 2680.03   266.4 2686.05   323.6 2719.39
   338.7 2729.92   353.7  2738.6   374.7 2752.92   386.8 2760.02   396.1 2767.14
   422.9 2783.86   449.1 2804.15   462.4 2815.95   497.3 2843.69508.2607 2850.01
#Mann= 3 ,-1,0
       0      .1       0   197.2    .045       0  208.35      .1       0
Bank Sta=197.2,208.35
XS Rating Curve= 0 ,0
Exp/Cntr(USF)=0,0
Exp/Cntr=0.3,0.1

Type RM Length L Ch R = 1 ,868     ,172.2,172.4,173.3
XS GIS Cut Line= 2
2373974.36314589702305.9996528122374402.54893799 702254.86460415
#Sta/Elev= 30
       0 2761.82     9.9 2758.54    37.7 2740.63    50.2 2736.66    66.3 2723.53
    74.3  2719.4   106.7  2695.7   120.1 2688.11   146.8 2664.73     163 2654.07
     175 2642.96   195.2 2632.76   200.3 2632.11   209.3 2632.93   219.4 2635.39
   223.4 2638.55   231.4  2647.2   243.5 2663.18   263.7 2676.72   280.2 2693.14
   291.9 2707.43   299.9 2729.56     304 2739.23     308 2743.76     316 2746.52
   328.1 2754.49   348.3 2763.62   371.7 2776.76   416.8 2806.52431.2283 2818.55
#Mann= 3 ,-1,0
       0      .1       0   195.2    .045       0   209.3      .1       0
Bank Sta=195.2,209.3
XS Rating Curve= 0 ,0
Exp/Cntr(USF)=0,0
Exp/Cntr=0.3,0.1

Type RM Length L Ch R = 1 ,696     ,143.6,143.3,142.8
XS GIS Cut Line= 3
2373984.51099204702452.0605564492374282.36885662702450.157311308
2374443.19307104702374.027505665
#Sta/Elev= 30
       0 2756.69    23.7 2742.29    39.7 2728.05    51.7 2720.12    63.7 2710.11
    83.7 2697.86   119.7 2671.54   155.7 2647.93   175.7 2633.26   195.7 2616.42
   199.7 2614.58   221.1 2612.04   227.7 2611.17  232.86    2612   243.7 2622.51
   247.7 2627.61   255.7 2640.45   259.7 2643.89   283.7 2656.13   291.7 2660.98
   299.9 2667.69     312 2673.14   375.1 2712.03   383.9 2720.35   401.6 2734.33
   414.1 2741.79   420.1  2750.3   423.1 2753.11   434.1 2759.18 475.797  2790.3
#Mann= 3 ,-1,0
       0      .1       0   221.1    .045       0  232.86      .1       0
Bank Sta=221.1,232.86
XS Rating Curve= 0 ,0
Exp/Cntr(USF)=0,0
Exp/Cntr=0.3,0.1

Type RM Length L Ch R = 1 ,552     ,170,170.8,170.9
XS GIS Cut Line= 4
2373991.17235004  702595.75556462374345.17594628702589.094206606
2374418.45088421702590.9974517472374493.62906728702665.224012248
#Sta/Elev= 30
       0 2751.85      41 2720.72    74.2 2698.56    92.2 2683.46     137 2642.28
     149 2634.15     157 2630.79   172.4 2619.52   194.1 2598.35     201 2597.43
  209.67 2598.45     217 2600.36     237 2600.53     241 2601.68     253 2609.57
     261 2611.31   285.1 2629.06   308.3 2649.27   313.1  2651.9   325.1 2664.76
   333.1 2668.91   341.2 2678.97   357.1 2691.56   369.1 2707.24   421.1 2740.11
   427.4 2745.72   436.2 2757.88   464.6 2774.92   523.5 2803.12533.0132 2809.32
#Mann= 3 ,-1,0
       0      .1       0   194.1    .045       0  209.67      .1       0
Bank Sta=194.1,209.67
XS Rating Curve= 0 ,0
Exp/Cntr(USF)=0,0
Exp/Cntr=0.3,0.1

Type RM Length L Ch R = 1 ,382     ,116.4,117.8,117.4
XS GIS Cut Line= 3
2374042.16790035702739.9482713552374371.69100596702768.391318365
2374454.93894843702767.003852657
#Sta/Elev= 30
       0 2680.38      10 2674.52    30.1 2660.19    50.2 2648.84    62.2 2640.57
   102.4  2616.5   113.9 2610.82   130.5 2594.85   142.5 2586.07   150.6 2583.12
   158.6 2585.79   162.6 2585.09   174.7 2577.99   185.4 2575.01   194.7 2573.73
   198.7  2574.8   214.8 2590.95   226.8 2600.16   232.1  2607.6   242.9 2617.62
     255 2632.96     267 2650.27     271 2654.55   319.2 2698.89   323.2 2704.57
   327.2 2712.57   331.2 2717.43   379.2 2761.24   405.3 2782.85414.0079 2794.67
#Mann= 3 ,-1,0
       0      .1       0   185.4    .045       0   198.7      .1       0
Bank Sta=185.4,198.7
XS Rating Curve= 0 ,0
Exp/Cntr(USF)=0,0
Exp/Cntr=0.3,0.1

Type RM Length L Ch R = 1 ,264     ,54.7,56.7,58.1
XS GIS Cut Line= 4
2374034.98330538702787.4282677782374148.16378966702849.841780216
2374155.92815006702854.3212189082374350.63441853702852.230814185
#Sta/Elev= 30
       0 2666.54    37.9 2635.56      45 2630.25    56.2 2623.41    74.4 2609.88
    83.6  2604.7   106.4 2589.54   124.7 2575.46   142.5 2570.39   153.5 2561.18
   158.5 2560.46   163.3 2561.12   166.5 2561.81   174.5 2565.93   182.5 2567.01
   198.5  2576.3   214.5 2589.99   230.6 2606.73   246.5 2619.26   274.5 2644.56
   278.5 2646.89   282.5 2651.03   286.5 2657.87   290.5 2663.53   294.5 2667.87
   298.5 2673.39   302.5 2683.61   306.5  2690.2   327.4 2709.44   332.9 2715.19
#Mann= 3 ,-1,0
       0      .1       0   153.5    .045       0   163.3      .1       0
Bank Sta=153.5,163.3
XS Rating Curve= 0 ,0
Exp/Cntr(USF)=0,0
Exp/Cntr=0.3,0.1

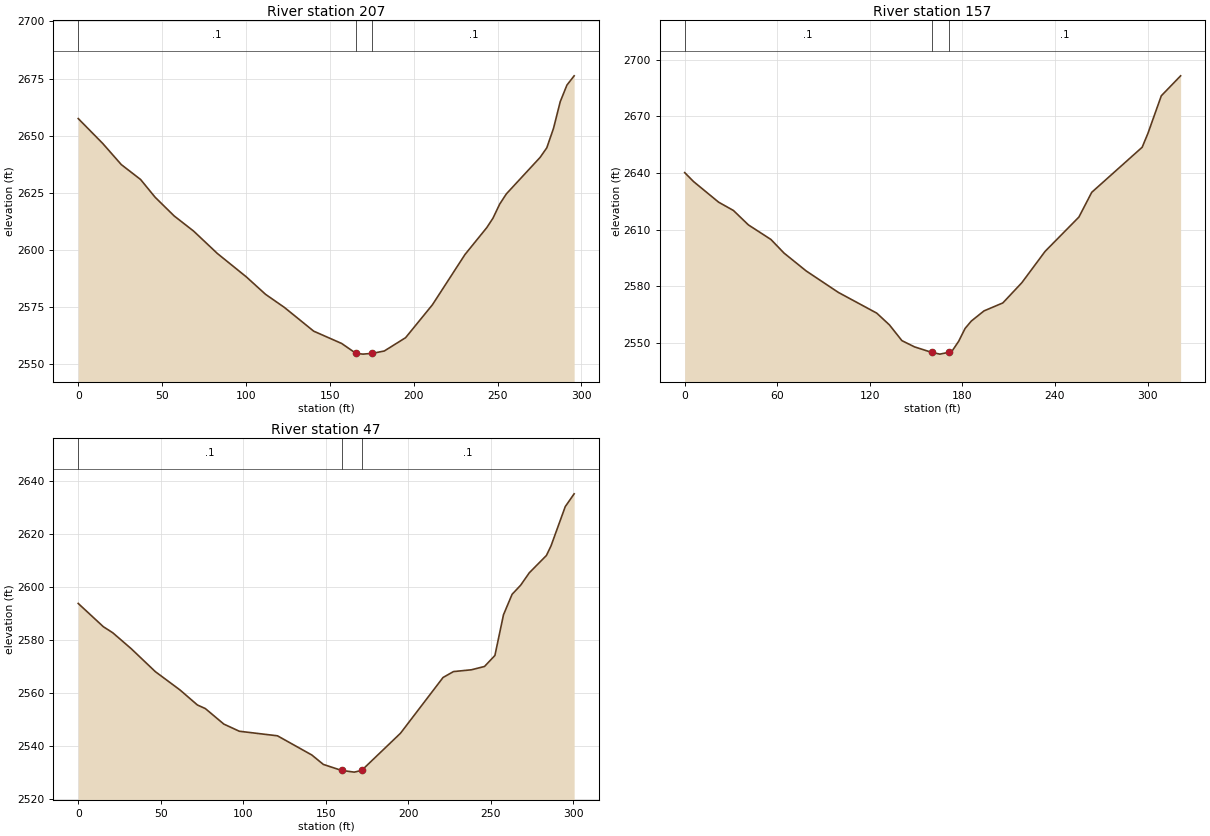
Type RM Length L Ch R = 1 ,207     ,48.8,50.7,46.4
XS GIS Cut Line= 4
2374028.26098794702813.2443364242374154.84992536702903.818586771
 2374190.3270798702916.4506038822374292.45828198702909.193913202
#Sta/Elev= 30
       0 2657.48    14.6 2646.58    25.7 2637.31    37.2 2630.78    45.8 2623.06
    57.2 2614.83    68.8 2608.19      83 2598.36   100.2 2588.16   111.7 2580.49
   122.9 2574.78   140.4 2564.36   157.1 2558.96   165.6 2554.63   169.8  2554.3
   175.4 2554.64   182.5 2555.67   195.2  2561.5   211.2 2575.92   230.6 2597.92
   243.6  2609.7   247.3 2613.85   251.3    2620   255.3  2624.5   275.4 2640.46
   279.4 2644.68   283.4  2653.2   287.4 2664.85   291.4 2672.14   295.7 2676.19
#Mann= 3 ,-1,0
       0      .1       0   165.6    .045       0   175.4      .1       0
Bank Sta=165.6,175.4
XS Rating Curve= 0 ,0
Exp/Cntr(USF)=0,0
Exp/Cntr=0.3,0.1

Type RM Length L Ch R = 1 ,157     ,111.7,109.9,108.2
XS GIS Cut Line= 4
2374028.98697612702850.9455279822374080.32320731702927.256141913
2374200.33899104702952.2305246542374304.39891913702927.949874767
#Sta/Elev= 30
       0 2640.16     5.7 2635.44      22 2624.48    31.6 2620.08    41.3 2612.44
    55.9 2604.72    64.4  2597.5    78.8 2588.01    99.6 2576.67   124.5 2565.68
   132.7 2559.46   140.8 2551.11     149  2547.8  159.98 2544.93   165.4 2543.97
  171.42 2544.97   173.5 2545.83   177.6 2550.82   181.7 2557.54   185.8 2561.52
     194 2566.88   206.2  2571.1   218.5  2581.8   233.6 2598.43   255.5  2616.6
   263.8  2629.7   296.5 2653.59   300.2 2660.87   308.9 2680.85321.4131 2691.43
#Mann= 3 ,-1,0
       0      .1       0  159.98    .045       0  171.42      .1       0
Bank Sta=159.98,171.42
XS Rating Curve= 0 ,0
Exp/Cntr(USF)=0,0
Exp/Cntr=0.3,0.1

Type RM Length L Ch R = 1 ,47      ,,,
XS GIS Cut Line= 5
2374021.30516438702949.9602524722374097.60996226703025.024407754
2374129.58469947703051.4771776722374159.30693665703048.456791884
2374253.07203157702970.405895391
#Sta/Elev= 30
       0 2593.71    15.2 2584.95    20.9 2582.67    32.1 2576.65    46.7 2568.01
    61.6 2561.12    72.2 2555.43      77 2554.08    88.2 2548.23    97.6 2545.53
   120.7 2543.81   141.5 2536.58   148.5 2533.02 159.4942530.766   167.2 2530.12
171.67632530.759   195.2 2544.77     221  2565.8   227.3 2568.02   238.2  2568.7
   246.1 2569.95   252.4 2574.09   257.6 2589.44   262.8 2597.14     268 2600.58
   273.2 2605.24   283.6 2611.79   286.4 2615.42     295  2630.2   300.4 2635.03
#Mann= 3 ,0,0
       0      .1       0 159.494    .045       0171.6763      .1       0
Bank Sta=159.494,171.6763
XS Rating Curve= 0 ,0
Exp/Cntr(USF)=0,0
Exp/Cntr=0.3,0.1
LCMann Table=0

Chan Stop Cuts=-1
Use User Specified Reach Order=0
Composite Channel Slope=5